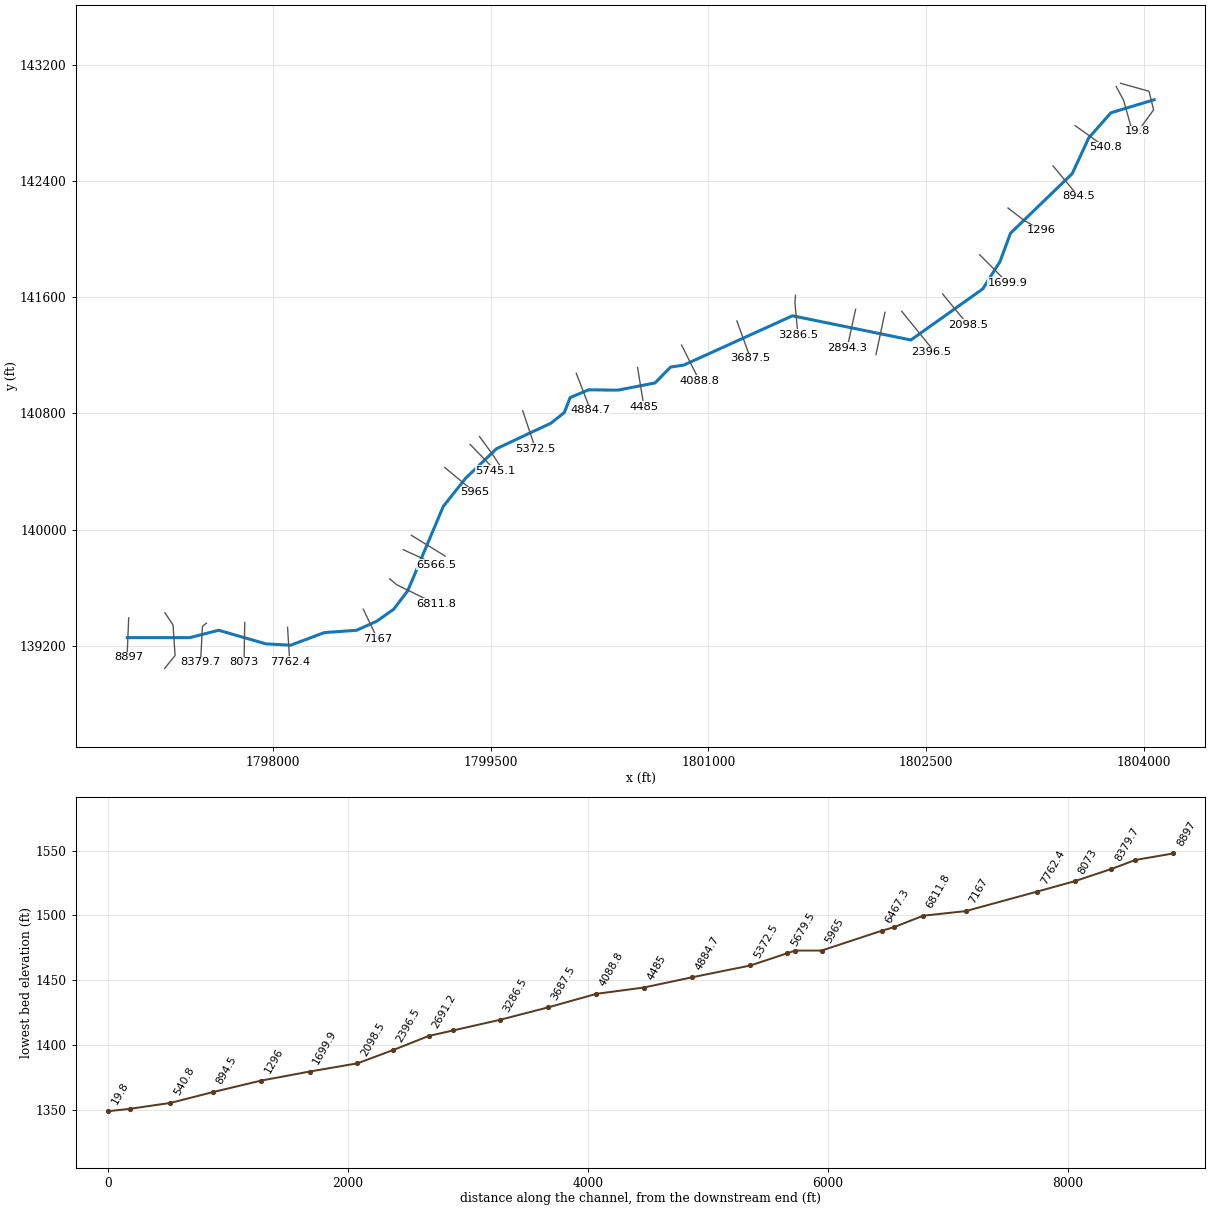
--- Sugarcamp Branch.prj (project) ---

Proj Title=Sugarcamp Branch
Current Plan=p01
Default Exp/Contr=0,0
English Units
Geom File=g01
Flow File=f01
Plan File=p01
BEGIN DESCRIPTION:
END DESCRIPTION:
DSS Export Rating Curves= 0
DSS Export Rating Curve Sorted= 0
DSS Export Volume Flow Curves= 0
DXF OffsetX= 0
DXF OffsetY= 0
DXF ScaleX= 0
DXF ScaleY= 0

--- Sugarcamp Branch.p01 (plan) ---

Plan Title=Floodplain
Program Version=4.00
Geom File=g01
Flow File=f01
K Sum by GR=0
Std Step Tol=0.01
Critical Tol=0.01
Num of Std Step Trials=20
Max Error Tol=0.3
Flow Tol Ratio=0.001
Split Flow NTrial=30
Split Flow Tol=0.02
Split Flow Ratio=0.02
Log Output Level=0
Friction Slope Method=1
Unsteady Friction Slope Method=2
Unsteady Bridges Friction Slope Method=1
Global Log Level=0
CheckData=False
Run HTab=0
Run UNet=0
Run PostProcess=0
UNET Theta=0
UNET Theta Warmup=0
UNET ZTol=0
UNET ZSATol=0
UNET MxIter=0
UNET MaxInSteps=0
UNET DtIC=0
UNET DtMin=0
UNET MaxCRTS=0
UNET WFStab=0
UNET SFStab=0
UNET WFX=0
UNET SFX=0
UNET DSS MLevel=0
UNET DZMax Abort=0
UNET Convert EG Bridges=0
UNET Use Existing IB Tables=0
UNET Froude Limit=0
UNET Froude Power=0
Write IC File=0
Echo Input=False
Echo Output=False
Write Detailed=0

--- Sugarcamp Branch.f01 (steady flow) ---

Flow Title=NFF Regression Equation
Program Version=4.00
Number of Profiles=1
Profile Names=P100yr
River Rch & RM=Sugarcamp Branch,Main      ,8897
561.8702
River Rch & RM=Sugarcamp Branch,Main      ,7762.4
623.1979
River Rch & RM=Sugarcamp Branch,Main      ,6811.8
662.3963
River Rch & RM=Sugarcamp Branch,Main      ,5965
735.6639
River Rch & RM=Sugarcamp Branch,Main      ,5372.5
804.1725
River Rch & RM=Sugarcamp Branch,Main      ,2691.2
872.4740
River Rch & RM=Sugarcamp Branch,Main      ,2396.5
964.3888
River Rch & RM=Sugarcamp Branch,Main      ,203.3
995.3272
Boundary for River Rch & Prof#=Sugarcamp Branch,Main      ,1
Up Type=0
Dn Type=3
Dn Slope=0.01575

--- Sugarcamp Branch.g01 (geometry) ---

Geom Title=Geometry
Program Version=4.00

River Reach=Sugarcamp Branch,Main
Reach XY= 30
     1796996.226       139255.86     1797426.493      139255.606
     1797625.791      139306.676     1797951.044       139213.04
     1798121.202      139203.522     1798354.287      139290.548
     1798575.809      139306.371     1798713.956      139368.446
     1798831.411      139451.213     1798928.175      139578.405
     1799173.401      140160.359     1799329.128      140356.101
     1799540.267      140557.412     1799913.924      140732.756
     1800007.181      140806.513     1800047.055      140909.686
      1800174.54      140962.918      1800375.98      140960.603
     1800632.362        141010.4     1800738.278      141119.412
     1800830.426      141133.459     1801578.736      141472.926
     1802394.628      141306.155      1802890.01      141658.521
     1803008.682       141847.18     1803080.483      142041.461
     1803506.246      142452.725     1803619.694      142698.579
     1803772.446      142871.414     1804069.692       142961.02

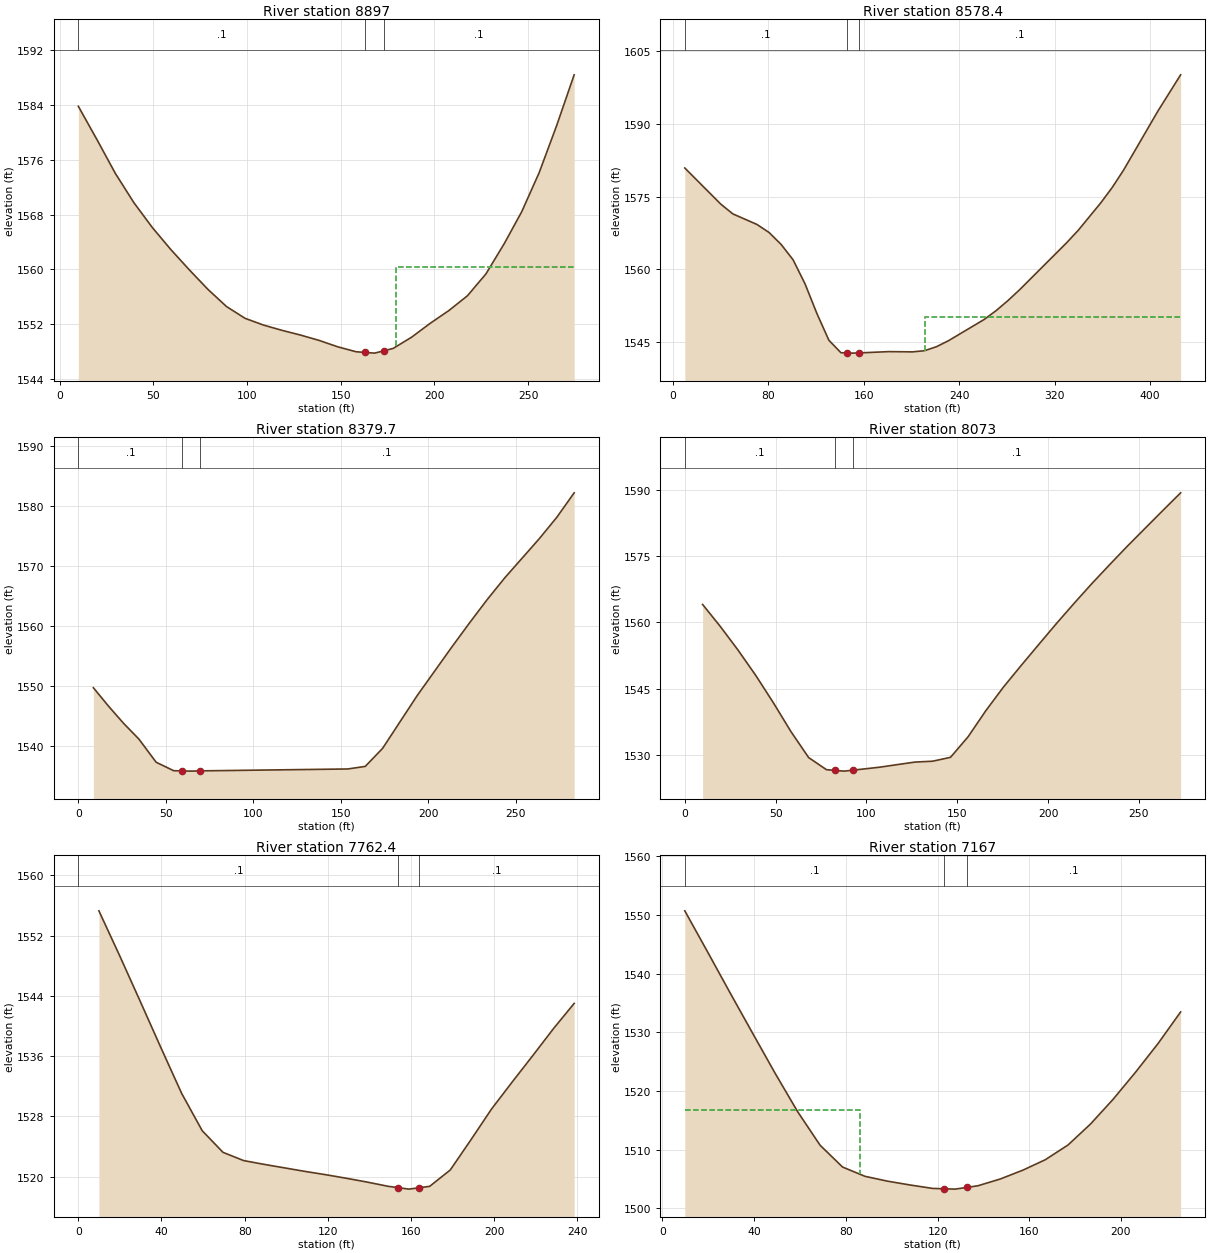
Type RM Length L Ch R = 1 ,8897    ,316.4,318.5,320.7
XS GIS Cut Line= 3
     1797006.226       139392.36      1796996.31      139155.227
     1797006.226       139119.36
#Sta/Elev= 30
     9.9  1583.8    19.8 1578.96    29.7 1573.99    39.6 1569.72    49.4 1566.11
    59.3 1562.89    69.2 1559.92    79.1 1557.08      89 1554.58    98.9 1552.86
   108.8 1551.87   118.7  1551.1   128.6 1550.41   138.4 1549.64   148.3 1548.71
   158.2 1547.98   163.1 1547.88   168.1 1547.78   173.1 1548.13     178 1548.47
   187.9 1550.12   197.8 1552.14   207.7 1553.99   217.6 1556.14   227.5 1559.34
   237.3 1563.77   246.6 1568.41   255.9  1574.1   265.2 1580.94   274.6 1588.39
#Mann= 3 , 0 , 0
     9.9      .1       0   163.1    .045       0   173.1      .1       0
#XS Ineff= 2 , 0
                           179.7          1560.3
Permanent Ineff=
       F       F
Bank Sta=163.1,173.1
XS Rating Curve= 0 ,0
Exp/Cntr=0.3,0.1

Type RM Length L Ch R = 1 ,8578.4  ,201.4,198.7,196.1
XS GIS Cut Line= 4
     1797255.701      139426.588     1797311.665      139342.643
     1797325.656      139132.779     1797253.953      139043.587
#Sta/Elev= 30
    10.1 1580.92    40.4 1573.43    50.4 1571.44    70.6 1569.26    80.7 1567.61
    90.8 1565.15   100.9 1561.95   110.9 1556.99   120.9 1550.83   130.9 1545.34
     141 1542.77     146 1542.73     151 1542.69     156 1542.73     181    1543
     201 1542.95   211.1 1543.19   221.1 1544.02   231.1 1545.25   261.1 1549.65
   271.2 1551.49   281.2 1553.59   291.2 1555.89   330.3 1565.52   339.8 1568.03
   358.9 1573.76   368.4 1576.91     378 1580.53   406.6 1592.65   425.7 1600.16
#Mann= 3 , 0 , 0
    10.1      .1       0     146    .045       0     156      .1       0
#XS Ineff= 2 , 0
                          211.41         1550.07
Permanent Ineff=
       F       F
Bank Sta=146,156
XS Rating Curve= 0 ,0
Exp/Cntr=0.3,0.1

Type RM Length L Ch R = 1 ,8379.7  ,305.7,306.7,307.7
XS GIS Cut Line= 3
     1797541.266      139355.313     1797514.227      139333.775
     1797501.161      139085.274
#Sta/Elev= 20
     8.6 1549.69    17.3  1546.6    25.9 1543.73    34.6 1541.12    44.5 1537.24
    54.5 1535.83    59.4 1535.79    64.4 1535.76    69.4  1535.8     154 1536.12
     164 1536.55   173.9 1539.56   193.8 1548.43   213.7 1556.58   223.7 1560.56
   233.6 1564.38   243.6    1568   263.5  1574.6   273.5 1578.17   283.4 1582.25
#Mann= 3 , 0 , 0
       0      .1       0    59.4    .045       0    69.4      .1       0
Bank Sta=59.4,69.4
XS Rating Curve= 0 ,0
Exp/Cntr=0.3,0.1

Type RM Length L Ch R = 1 ,8073    ,308.9,310.5,312.1
XS GIS Cut Line= 3
     1797805.521      139360.349     1797803.112       139223.87
     1797800.703      139087.391
#Sta/Elev= 30
     9.8 1564.09    19.5 1559.13    29.2 1553.81      39 1548.05    48.8 1541.79
    58.5 1535.24    68.2 1529.38      78 1526.64    82.8 1526.47    87.7 1526.31
    92.8 1526.54    97.5 1526.75   107.3  1527.2     117 1527.79   126.7 1528.36
   136.5 1528.56   146.3 1529.44     156 1534.11   165.7 1539.98   175.5 1545.39
   185.3  1550.3     195 1555.07   204.7  1559.8   214.5 1564.41   224.2 1568.85
     234 1573.14   243.7 1577.31   253.5 1581.37   263.2 1585.38     273 1589.39
#Mann= 3 , 0 , 0
       0      .1       0    82.8    .045       0    92.8      .1       0
Bank Sta=82.8,92.8
XS Rating Curve= 0 ,0
Exp/Cntr=0.3,0.1

Type RM Length L Ch R = 1 ,7762.4  ,587.3,595.5,603.7
XS GIS Cut Line= 2
     1798100.524      139326.177     1798115.719      139088.113
#Sta/Elev= 26
     9.9 1555.28    19.9 1549.31    29.8 1543.25    39.8 1537.07    49.7 1531.05
    59.6 1526.09    69.6 1523.22    79.5 1522.13    89.5 1521.62    99.4 1521.15
   109.3 1520.68   119.3 1520.24   129.2 1519.77   139.2 1519.26   149.1 1518.71
     154 1518.53     159 1518.34     164 1518.52     169 1518.71   178.9 1520.88
   188.9 1524.91   198.8 1528.99   208.7 1532.56   218.7  1536.1   228.6 1539.66
   238.5 1542.99
#Mann= 3 , 0 , 0
       0      .1       0     154    .045       0     164      .1       0
Bank Sta=154,164
XS Rating Curve= 0 ,0
Exp/Cntr=0.3,0.1

Type RM Length L Ch R = 1 ,7167    ,341.7,355.2,368.6
XS GIS Cut Line= 2
      1798622.24      139451.541     1798719.745      139247.667
#Sta/Elev= 25
     9.8 1550.69    19.7 1543.72    29.5 1536.75    39.3 1529.89    49.1 1523.07
      59 1516.47    68.8 1510.75    78.6 1507.03    88.4 1505.45    98.3 1504.62
   108.1 1503.97   117.9 1503.39   122.7 1503.33   127.7 1503.27   132.7 1503.56
   137.6 1503.84   147.4    1505   157.2  1506.5     167 1508.28   176.9 1510.79
   186.7 1514.36   196.5 1518.55   206.3 1523.17   216.2  1528.1     226 1533.46
#Mann= 3 , 0 , 0
     9.8      .1       0   122.7    .045       0   132.7      .1       0
#XS Ineff= 2 , 0
           86.41 1516.83
Permanent Ineff=
       F       F
Bank Sta=122.7,132.7
XS Rating Curve= 0 ,0
Exp/Cntr=0.3,0.1

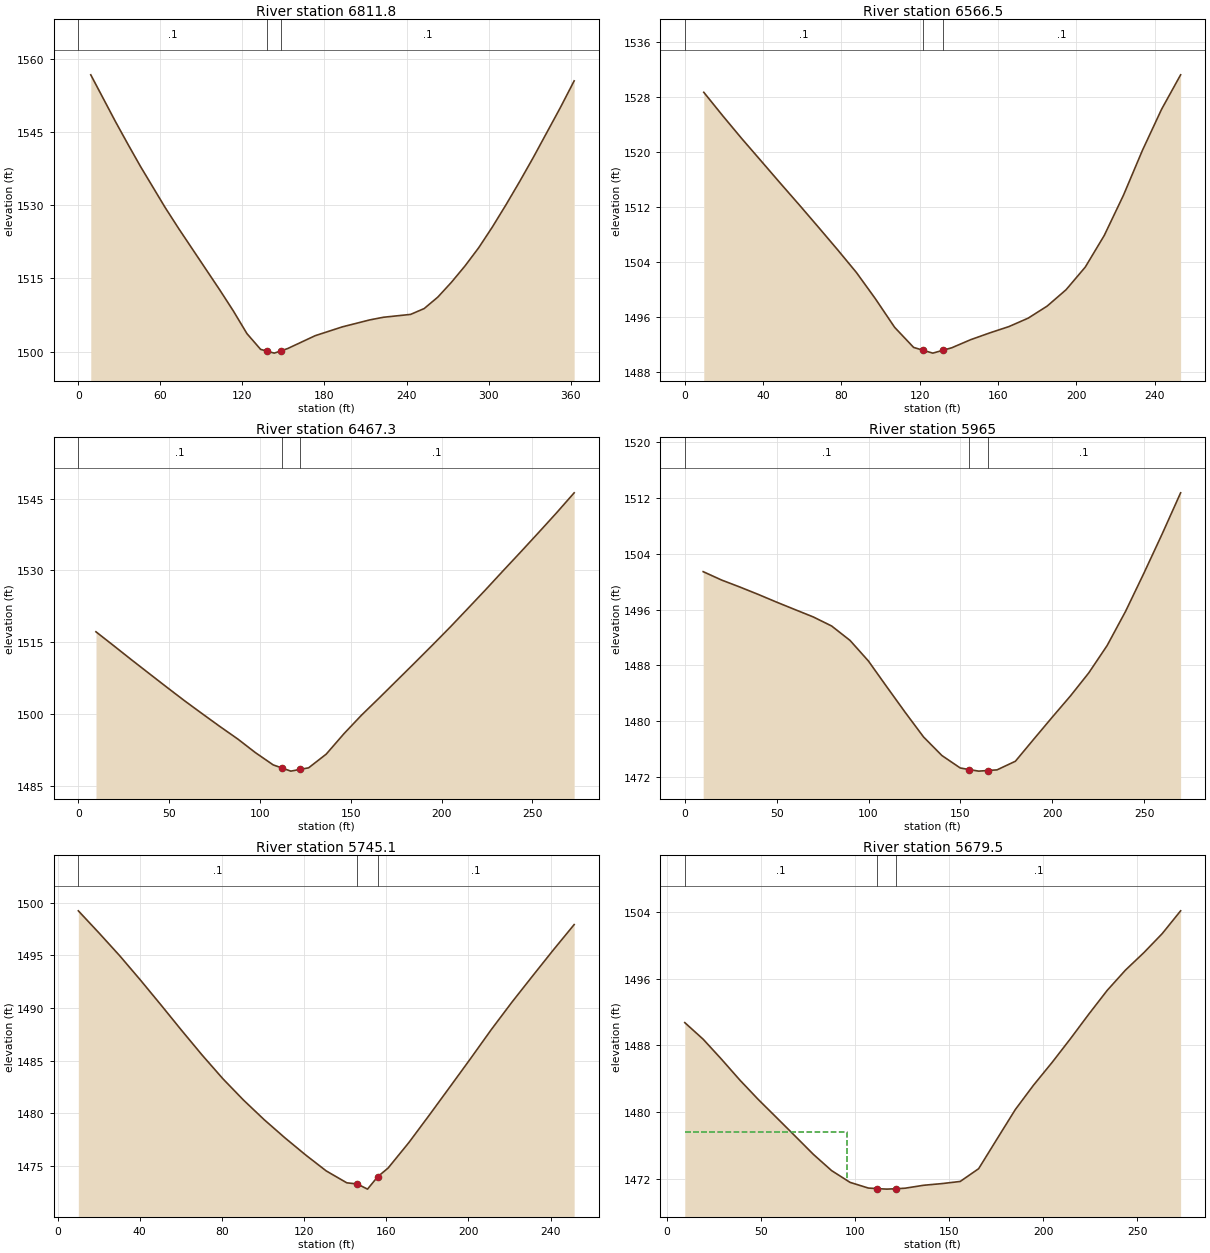
Type RM Length L Ch R = 1 ,6811.8  ,244.9,245.3,245.8
XS GIS Cut Line= 3
     1798803.733      139660.448     1798852.706      139619.959
     1799121.162      139488.264
#Sta/Elev= 30
     9.1 1556.66    27.2 1547.06    36.3 1542.44    45.4 1537.93    63.5 1529.49
    73.5 1525.14   103.4 1512.63   113.4  1508.3   123.3 1503.68   133.3 1500.45
   138.3 1500.06   143.3 1499.68   148.3 1500.16   153.2 1500.63   173.2 1503.25
   193.1 1505.06   213.1 1506.48     223 1507.02     243 1507.61   252.9  1508.8
   262.9 1511.15   272.9  1514.2   282.8 1517.54   292.8 1521.26   302.8 1525.51
   312.7 1530.03   322.7 1534.79   332.7 1539.73   352.6    1550   362.6 1555.42
#Mann= 3 , 0 , 0
       0      .1       0   138.3    .045       0   148.3      .1       0
Bank Sta=138.3,148.3
XS Rating Curve= 0 ,0
Exp/Cntr=0.3,0.1

Type RM Length L Ch R = 1 ,6566.5  ,101.6,99.2,96.7
XS GIS Cut Line= 2
     1798897.027      139861.822     1799127.493       139756.72
#Sta/Elev= 28
     9.7 1528.69    19.5 1525.24    29.2 1521.93      39 1518.71    48.7 1515.51
    58.5 1512.32    68.2 1509.11    77.9 1505.86    87.7 1502.49    97.4 1498.67
   107.2 1494.53   116.9 1491.61   121.7  1491.2   126.7 1490.78   131.7 1491.18
   136.4 1491.56   146.1 1492.74   155.9 1493.73   165.6 1494.64   175.4 1495.86
   185.1 1497.61   194.8    1500   204.6 1503.29   214.3 1507.89   224.1 1513.73
   233.8 1520.26   243.6 1526.24   253.3 1531.23
#Mann= 3 , 0 , 0
       0      .1       0   121.7    .045       0   131.7      .1       0
Bank Sta=121.7,131.7
XS Rating Curve= 0 ,0
Exp/Cntr=0.3,0.1

Type RM Length L Ch R = 1 ,6467.3  ,505.4,502.3,499.2
XS GIS Cut Line= 3
     1798954.012      139960.338     1799070.293      139888.847
     1799186.602      139817.401
#Sta/Elev= 30
     9.7  1517.2    19.5 1514.29    29.2 1511.38      39 1508.49    48.8 1505.61
    58.5  1502.8    68.3 1500.08      78 1497.42    87.8 1494.82    97.5 1491.98
   107.3 1489.42     112 1488.79     117 1488.12     122 1488.47   126.8 1488.81
   136.5 1491.67   146.3 1495.95     156 1499.83   165.8 1503.44   175.5 1507.08
   185.3 1510.75     195 1514.43   204.8  1518.2   214.5 1522.07   224.3    1526
     234 1529.98   243.8 1533.95   253.5 1537.94   263.3 1542.02     273  1546.2
#Mann= 3 , 0 , 0
       0      .1       0     112    .045       0     122      .1       0
Bank Sta=112,122
XS Rating Curve= 0 ,0
Exp/Cntr=0.3,0.1

Type RM Length L Ch R = 1 ,5965    ,221.8,219.8,217.8
XS GIS Cut Line= 2
     1799183.211      140427.859     1799390.884      140255.642
#Sta/Elev= 29
      10 1501.44      20 1500.24      30 1499.23      40 1498.17      50 1497.06
      60 1495.99    69.9 1494.94    79.9 1493.64    89.9 1491.57    99.9 1488.62
   109.9 1484.91   119.9 1481.25   129.9 1477.71   139.9 1475.04   149.9 1473.25
   154.9 1473.02   159.9  1472.8   164.9 1472.89   169.9 1472.98   179.9 1474.22
   189.9 1477.39   199.8  1480.5   209.8 1483.58   219.8  1486.9   229.8 1490.83
   239.8 1495.72   249.8 1501.21   259.8 1506.88   269.8 1512.76
#Mann= 3 , 0 , 0
       0      .1       0   154.9    .045       0   164.9      .1       0
Bank Sta=154.9,164.9
XS Rating Curve= 0 ,0
Exp/Cntr=0.3,0.1

Type RM Length L Ch R = 1 ,5745.1  ,68.4,65.6,61.9
XS GIS Cut Line= 2
     1799358.474      140586.456     1799533.303      140405.701
#Sta/Elev= 27
    10.1 1499.24    20.1 1497.15    30.2 1494.98    40.2 1492.69    50.3  1490.3
    60.4 1487.87    70.4 1485.52    80.5 1483.27    90.5 1481.25   100.6 1479.38
   110.6 1477.67   120.7 1476.04   130.8 1474.51   140.8 1473.38   145.9 1473.27
   150.9 1472.78   155.9 1473.97   160.9 1474.78     171  1477.2   181.1 1479.85
   191.1 1482.52   201.2 1485.23   211.2 1487.96   221.3 1490.58   231.4 1493.08
   241.4 1495.53   251.5 1497.93
#Mann= 3 , 0 , 0
    10.1      .1       0   145.9    .045       0   155.9      .1       0
Bank Sta=145.9,155.9
XS Rating Curve= 0 ,0
Exp/Cntr=0.3,0.1

Type RM Length L Ch R = 1 ,5679.5  ,313.1,307,302
XS GIS Cut Line= 3
     1799422.897      140640.483     1799503.804      140530.572
     1799579.471      140416.816
#Sta/Elev= 30
     9.7 1490.72    19.5 1488.72    29.2 1486.33      39 1483.82    48.7 1481.51
    58.5 1479.32    68.2 1477.14      78 1474.92    87.7 1472.97    97.5 1471.56
   107.2 1470.88     112 1470.81     117 1470.75     122  1470.8   126.7 1470.86
   136.5 1471.21   146.2 1471.41     156 1471.67   165.8  1473.2   175.5 1476.74
   185.3  1480.3     195 1483.23   204.8 1485.94   214.5 1488.77   224.3 1491.73
   234.1 1494.59   243.8 1497.02   253.6 1499.12   263.3 1501.39   273.1 1504.13
#Mann= 3 , 0 , 0
     9.7      .1       0     112    .045       0     122      .1       0
#XS Ineff= 2 , 0
           95.64 1477.62
Permanent Ineff=
       F       F
Bank Sta=112,122
XS Rating Curve= 0 ,0
Exp/Cntr=0.3,0.1

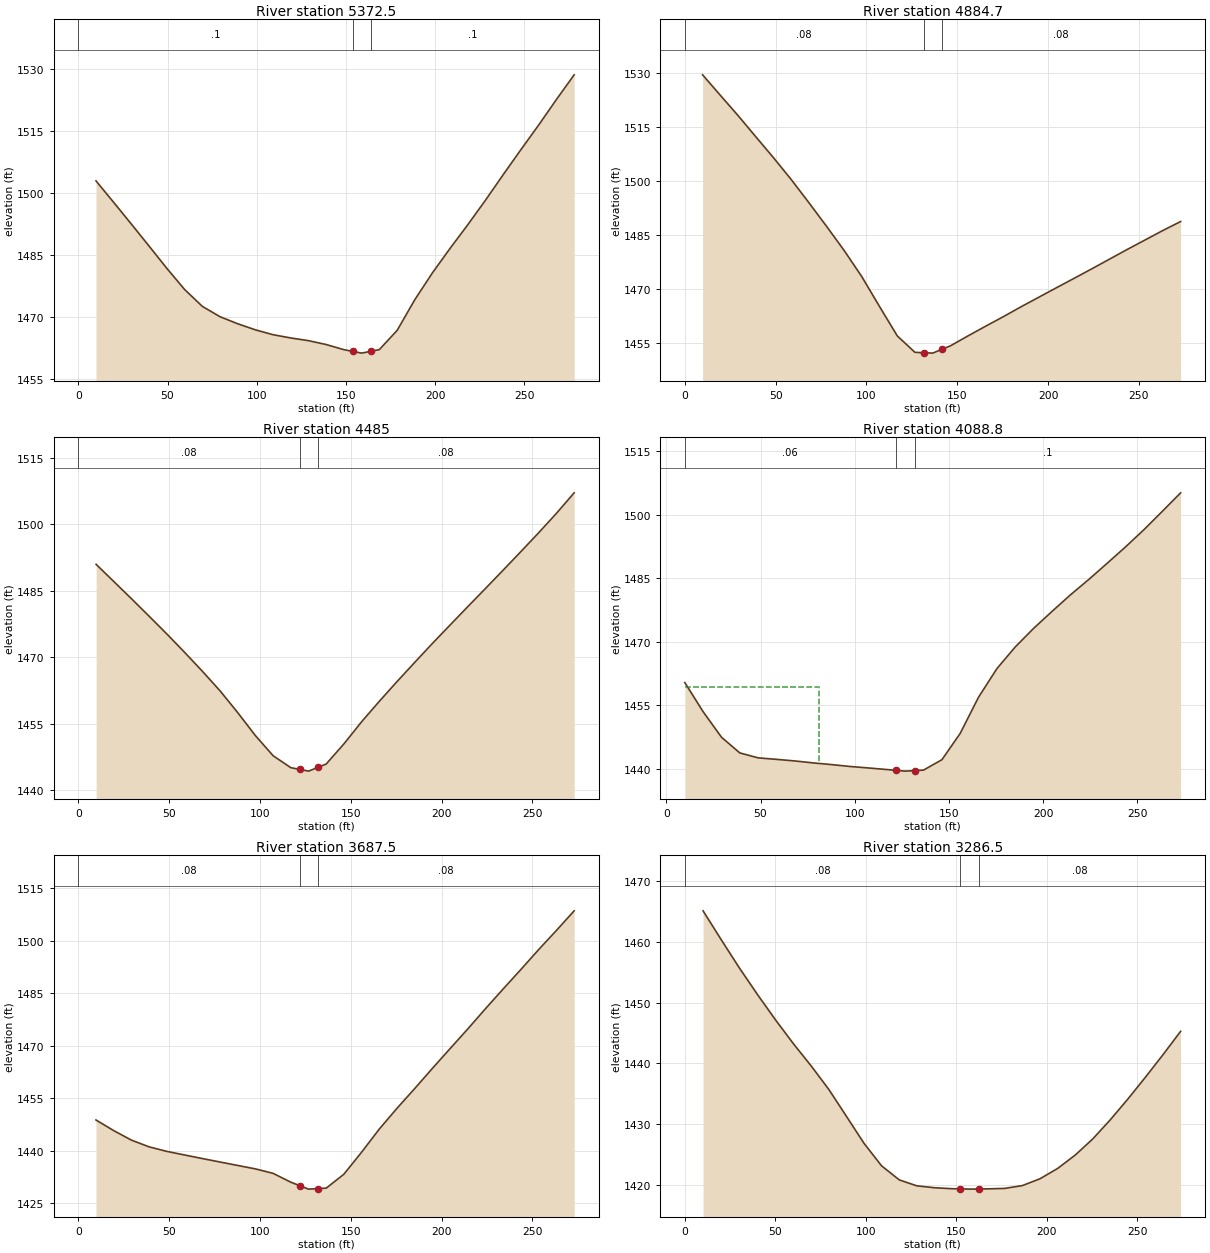
Type RM Length L Ch R = 1 ,5372.5  ,487.1,487.8,488.4
XS GIS Cut Line= 2
     1799720.122      140819.146     1799808.763      140555.755
#Sta/Elev= 30
     9.9 1502.99    19.9 1497.74    29.8 1492.49    39.7 1487.18    49.6 1481.82
    59.6 1476.68    69.5 1472.61    79.4 1470.11    89.3  1468.4    99.3 1466.92
   109.2 1465.74   119.1 1464.96     129 1464.31     139 1463.36   148.9 1462.12
   153.8 1461.71   158.8 1461.29   163.8 1461.72   168.7 1462.14   178.7  1466.8
   188.6 1474.23   198.5 1480.74   208.4 1486.67   218.4 1492.44   228.3 1498.37
   238.2 1504.53   248.1 1510.57   258.1 1516.56     268 1522.71   277.9 1528.66
#Mann= 3 , 0 , 0
       0      .1       0   153.8    .045       0   163.8      .1       0
Bank Sta=153.8,163.8
XS Rating Curve= 0 ,0
Exp/Cntr=0.3,0.1

Type RM Length L Ch R = 1 ,4884.7  ,403.9,399.7,395.5
XS GIS Cut Line= 3
     1800089.377      141076.321     1800138.652      140949.026
     1800187.928       140821.73
#Sta/Elev= 30
     9.8  1529.4    19.5 1523.76    29.3 1518.11      39 1512.27    48.7 1506.48
    58.5  1500.4    68.3 1493.93      78 1487.39    87.8  1480.6    97.5 1473.35
   107.2 1465.11     117 1456.93   126.7 1452.38   131.5 1452.26   136.5 1452.15
   141.5 1453.19   146.3 1454.18     156 1456.95   165.7 1459.64   175.5  1462.3
   185.2 1465.03     195 1467.69   204.7 1470.32   214.5 1472.95   224.2 1475.58
     234 1478.28   243.7 1480.95   253.5 1483.58   263.2 1486.18     273 1488.68
#Mann= 3 , 0 , 0
       0     .08       0   131.5    .045       0   141.5     .08       0
Bank Sta=131.5,141.5
XS Rating Curve= 0 ,0
Exp/Cntr=0.3,0.1

Type RM Length L Ch R = 1 ,4485    ,390.2,396.2,402.2
XS GIS Cut Line= 3
     1800511.522       141117.15     1800533.566      140982.442
      1800555.61      140847.733
#Sta/Elev= 30
     9.8 1490.93    19.5 1487.07    29.3 1483.16      39 1479.22    48.8  1475.2
    58.5 1471.09    68.2 1466.86      78 1462.42    87.7 1457.52    97.5  1452.3
   107.3 1447.75     117 1445.07   121.8 1444.69   126.8 1444.29   131.8 1445.12
   136.5  1445.9   146.3 1450.47     156 1455.44   165.8 1460.07   175.5  1464.5
   185.3 1468.85     195 1473.11   204.8 1477.29   214.5 1481.42   224.3 1485.54
     234 1489.66   243.7 1493.82   253.5 1498.07   263.3 1502.46     273 1507.06
#Mann= 3 , 0 , 0
       0     .08       0   121.8    .045       0   131.8     .08       0
Bank Sta=121.8,131.8
XS Rating Curve= 0 ,0
Exp/Cntr=0.3,0.1

Type RM Length L Ch R = 1 ,4088.8  ,403.7,401.3,399.1
XS GIS Cut Line= 3
     1800814.821      141271.049     1800875.866       141148.96
     1800936.912      141026.872
#Sta/Elev= 30
     9.8 1460.33    19.5 1453.46    29.3  1447.4      39  1443.7    48.8 1442.53
    58.5 1442.18    68.3  1441.8      78 1441.34    87.8 1440.94    97.5  1440.5
   107.2 1440.15     117 1439.78   121.8 1439.59   126.8  1439.4   131.8 1439.52
   136.5 1439.64   146.3  1442.1     156 1448.32   165.7 1456.84   175.5 1463.63
   185.3 1468.78     195 1473.14   204.7 1477.12   214.5 1481.04   224.3  1484.7
     234  1488.5   243.7 1492.35   253.5 1496.43   263.3 1500.78     273 1505.15
#Mann= 3 , 0 , 0
     9.8     .06       0   121.8    .045       0   131.8      .1       0
#XS Ineff= 2 , 0
           81.04 1459.23
Permanent Ineff=
       F       F
Bank Sta=121.8,131.8
XS Rating Curve= 0 ,0
Exp/Cntr=0.3,0.1

Type RM Length L Ch R = 1 ,3687.5  ,406.2,401,395.8
XS GIS Cut Line= 3
     1801195.864      141437.117     1801242.429      141308.805
     1801289.482       141180.67
#Sta/Elev= 30
     9.7 1448.75    19.5  1445.7    29.2 1442.99      39 1441.05    48.7 1439.76
    58.5 1438.73    68.2 1437.72      78 1436.72    87.7 1435.74    97.5 1434.75
   107.2 1433.48     117 1430.95   121.8 1429.97   126.7 1428.96   131.8 1429.11
   136.5 1429.25   146.2 1433.22     156 1439.55   165.7 1446.14   175.5 1452.11
   185.3 1457.79     195 1463.54   204.8 1469.23   214.5 1474.83   224.3 1480.66
     234 1486.28   243.8 1491.88   253.5 1497.52   263.3 1503.01     273 1508.59
#Mann= 3 , 0 , 0
       0     .08       0   121.8    .045       0   131.8     .08       0
Bank Sta=121.8,131.8
XS Rating Curve= 0 ,0
Exp/Cntr=0.3,0.1

Type RM Length L Ch R = 1 ,3286.5  ,398.4,392.2,386
XS GIS Cut Line= 3
     1801599.582      141614.055     1801595.513       141563.73
     1801616.332      141341.056
#Sta/Elev= 30
    10.1 1465.05    20.2 1460.28    30.3 1455.62    40.4 1451.22    50.5 1447.01
    60.2 1443.18    69.9 1439.58    79.7  1435.7    89.4  1431.3    99.1 1426.88
   108.8 1423.19   118.6 1420.88   128.3 1419.91     138  1419.6   147.7 1419.44
   152.4 1419.41   157.4 1419.37   162.4 1419.39   167.2 1419.41   176.9 1419.49
   186.6 1419.95   196.3 1421.06   206.1 1422.76   215.8 1424.95   225.5  1427.6
   235.2 1430.74     245 1434.18   254.7 1437.76   264.4 1441.45   274.1 1445.27
#Mann= 3 , 0 , 0
       0     .08       0   152.4    .045       0   162.4     .08       0
Bank Sta=152.4,162.4
XS Rating Curve= 0 ,0
Exp/Cntr=0.3,0.1

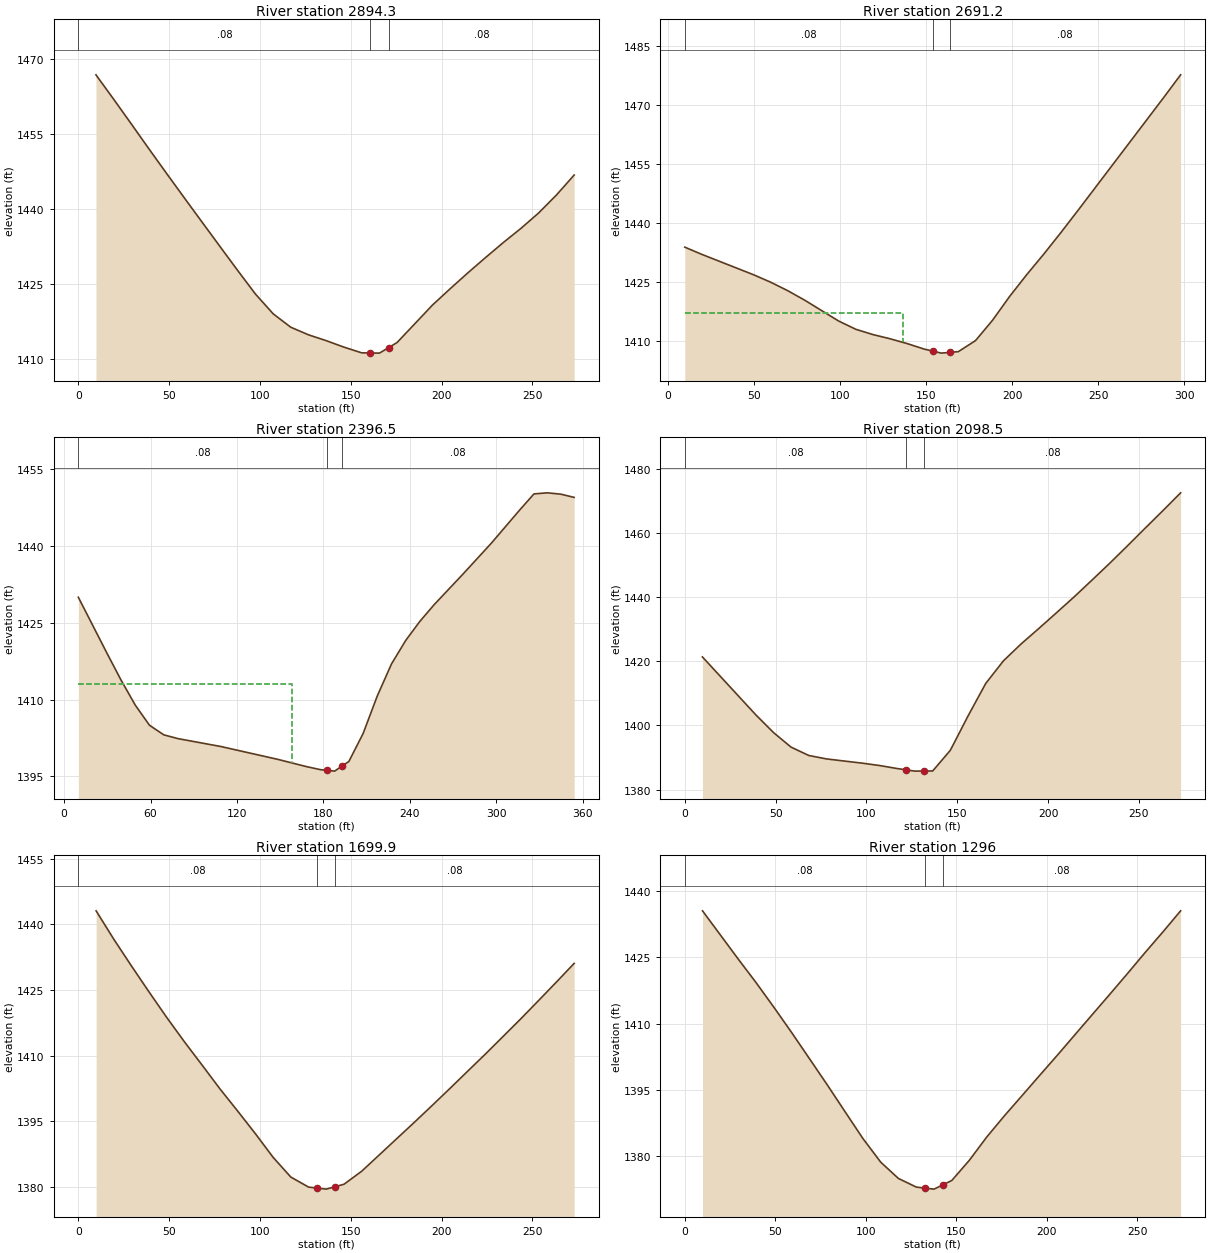
Type RM Length L Ch R = 1 ,2894.3  ,203,203.1,203.2
XS GIS Cut Line= 3
      1802013.65      141517.695      1801984.46      141384.353
     1801955.271       141251.01
#Sta/Elev= 30
     9.7 1466.76    19.5 1461.86    29.3 1456.88      39  1451.9    48.7    1447
    58.5  1442.1    68.3 1437.24      78 1432.45    87.8 1427.63    97.5 1422.96
   107.3 1418.99     117 1416.31   126.8 1414.79   136.5 1413.63   146.3 1412.33
     156  1411.2   160.8 1411.17   165.8 1411.14   170.8 1412.23   175.5 1413.26
   185.3 1417.02     195 1420.75   204.8 1424.03   214.5 1427.19   224.3 1430.27
     234 1433.24   243.8  1436.1   253.5 1439.17   263.3 1442.76     273 1446.73
#Mann= 3 , 0 , 0
       0     .08       0   160.8    .045       0   170.8     .08       0
Bank Sta=160.8,170.8
XS Rating Curve= 0 ,0
Exp/Cntr=0.3,0.1

Type RM Length L Ch R = 1 ,2691.2  ,276.2,294.8,313.3
XS GIS Cut Line= 2
        1802216.      141496.616     1802153.951      141205.367
#Sta/Elev= 25
     9.9  1433.8    19.9 1431.95    49.6 1426.83    59.6 1424.93    69.5 1422.78
    79.4 1420.36    99.3 1415.01   109.2 1412.93   119.1 1411.59     129 1410.53
     139  1409.3   148.9  1407.9   153.8 1407.39   158.8 1406.87   163.8 1407.06
   168.7 1407.24   178.7 1410.05   188.6 1415.23   198.5 1421.27   208.4 1426.79
   218.4 1432.07   228.3 1437.52   238.2 1443.14   287.9 1471.79   297.8  1477.6
#Mann= 3 , 0 , 0
     9.9     .08       0   153.8    .045       0   163.8     .08       0
#XS Ineff= 2 , 0
          136.41 1417.12
Permanent Ineff=
       F       F
Bank Sta=153.8,163.8
XS Rating Curve= 0 ,0
Exp/Cntr=0.3,0.1

Type RM Length L Ch R = 1 ,2396.5  ,297.9,297.9,298
XS GIS Cut Line= 3
      1802331.42      141503.424     1802536.857      141250.103
     1802533.768      141222.299
#Sta/Elev= 28
     9.9 1429.96    29.7 1419.09    39.5 1413.83    49.4 1408.93    59.3 1404.99
    69.2 1403.12    79.1 1402.38   108.7 1400.85   148.3 1398.34     168 1396.94
   177.9 1396.33   182.8 1396.19   187.8 1396.04   192.8 1396.99   197.7 1397.92
   207.6 1403.38   217.4 1410.68   227.3 1416.95   237.2 1421.55   247.1 1425.29
     257 1428.54   276.7 1434.41   296.5 1440.47   316.3 1446.98   326.2 1450.12
   335.5 1450.33   344.8 1450.07   354.1 1449.44
#Mann= 3 , 0 , 0
     9.9     .08       0   182.8    .045       0   192.8     .08       0
#XS Ineff= 2 , 0
          158.39 1412.99
Permanent Ineff=
       F       F
Bank Sta=182.8,192.8
XS Rating Curve= 0 ,0
Exp/Cntr=0.3,0.1

Type RM Length L Ch R = 1 ,2098.5  ,396.6,398.7,400.6
XS GIS Cut Line= 3
     1802613.471      141622.714     1802700.089      141517.218
     1802786.707      141411.721
#Sta/Elev= 30
     9.7 1421.36    19.5 1415.35    29.2 1409.39      39 1403.38    48.8 1397.81
    58.5 1393.25    68.3 1390.64      78 1389.58    87.7 1388.92    97.5 1388.27
   107.2 1387.52     117 1386.57   121.8 1386.17   126.7 1385.77   131.8  1385.8
   136.5 1385.82   146.2 1392.26     156 1403.01   165.7  1413.1   175.5 1420.18
   185.2 1425.42     195 1430.26   204.7 1435.15   214.5 1440.14   224.2  1445.3
     234 1450.57   243.8 1456.02   253.5  1461.5   263.3 1466.97     273  1472.5
#Mann= 3 , 0 , 0
       0     .08       0   121.8    .045       0   131.8     .08       0
Bank Sta=121.8,131.8
XS Rating Curve= 0 ,0
Exp/Cntr=0.3,0.1

Type RM Length L Ch R = 1 ,1699.9  ,401.3,403.9,409.1
XS GIS Cut Line= 3
     1802868.077      141893.603     1802964.369      141796.852
     1803060.149      141699.598
#Sta/Elev= 30
     9.8 1443.12    19.5 1436.64    29.3 1430.48      39 1424.52    48.8 1418.65
    58.5  1413.1    68.3 1407.73      78 1402.36    87.8 1397.26    97.5 1392.11
   107.3 1386.68     117 1382.19   126.8 1379.89   131.5 1379.67   136.5 1379.43
   141.5    1380   146.3 1380.55     156 1383.52   165.8  1387.3   175.5 1391.05
   185.3 1394.83     195 1398.65   204.8 1402.55   214.5 1406.47   224.3 1410.41
     234 1414.42   243.8 1418.48   253.5 1422.63   263.3 1426.85     273 1431.09
#Mann= 3 , 0 , 0
       0     .08       0   131.5    .045       0   141.5     .08       0
Bank Sta=131.5,141.5
XS Rating Curve= 0 ,0
Exp/Cntr=0.3,0.1

Type RM Length L Ch R = 1 ,1296    ,405.9,401.5,394.5
XS GIS Cut Line= 3
     1803063.855       142215.18      1803173.03      142131.045
     1803290.585      142062.133
#Sta/Elev= 30
     9.8 1435.58    19.7 1430.09    29.5 1424.66    39.4  1419.3    49.2 1413.74
    59.1 1407.96    68.9 1402.06    78.8 1396.09    88.6 1390.02    98.5 1383.92
   108.3 1378.58   118.1 1374.88     128 1372.92   132.8 1372.69   137.8 1372.46
   142.8 1373.46   147.6 1374.42   157.3    1379     167 1384.32   176.8 1389.14
   186.5 1393.69   196.2 1398.27     206 1402.85   215.7 1407.49   225.4 1412.11
   235.2 1416.77   244.9 1421.44   254.6 1426.18   264.4 1430.84   274.1 1435.58
#Mann= 3 , 0 , 0
       0     .08       0   132.8    .045       0   142.8     .08       0
Bank Sta=132.8,142.8
XS Rating Curve= 0 ,0
Exp/Cntr=0.3,0.1

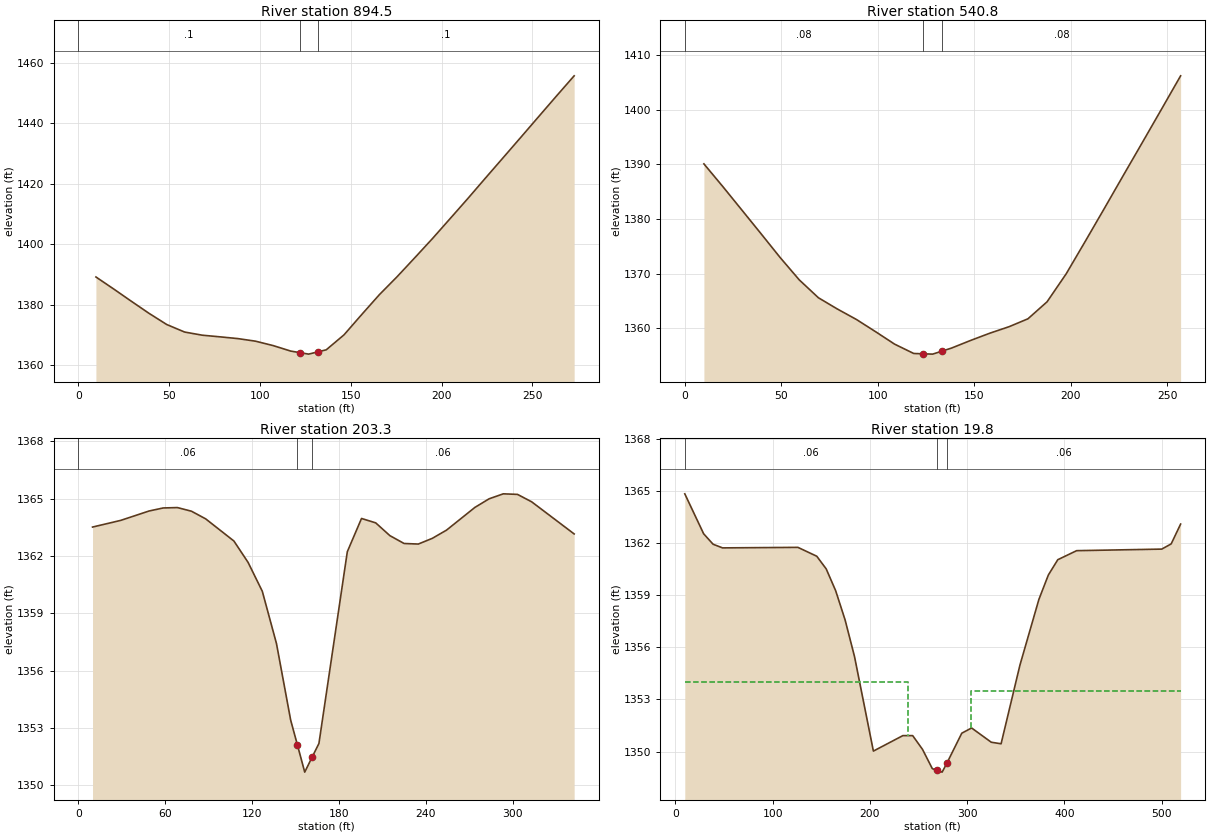
Type RM Length L Ch R = 1 ,894.5   ,348.6,353.7,358.9
XS GIS Cut Line= 3
     1803373.845      142505.045     1803461.035       142400.02
     1803548.225      142294.996
#Sta/Elev= 30
     9.7 1389.11    19.5 1385.12    29.2 1381.07      39 1377.05    48.7 1373.37
    58.5 1370.89    68.2 1369.85      78  1369.3    87.7 1368.73    97.5 1367.87
   107.3  1366.4     117 1364.58   121.8 1364.09   126.8 1363.58   131.8 1364.32
   136.5 1365.01   146.3 1369.97     156 1376.66   165.7 1383.22   175.5 1389.19
   185.2 1395.44     195 1401.83   204.7 1408.42   214.5  1415.1   224.2 1421.87
     234 1428.65   243.8 1435.44   253.5 1442.21   263.2 1448.95     273 1455.68
#Mann= 3 , 0 , 0
       0      .1       0   121.8    .045       0   131.8      .1       0
Bank Sta=121.8,131.8
XS Rating Curve= 0 ,0
Exp/Cntr=0.3,0.1

Type RM Length L Ch R = 1 ,540.8   ,352.2,337.5,322.6
XS GIS Cut Line= 2
     1803525.355      142783.177     1803734.294      142633.754
#Sta/Elev= 28
     9.9 1390.08    19.8 1385.88    29.6 1381.61    39.5 1377.29    49.4 1372.93
    59.3 1368.84    69.2 1365.57      79 1363.51    88.9 1361.59    98.8 1359.36
   108.7 1357.07   118.6 1355.36   123.4  1355.3   128.4 1355.24   133.4  1355.8
   138.3 1356.36   148.2 1357.76   158.1 1359.08     168 1360.26   177.8 1361.71
   187.7 1364.82   197.6 1369.94   207.5  1375.9   217.4 1381.93   227.2 1387.96
   237.1 1394.01     247 1400.09   256.9  1406.2
#Mann= 3 , 0 , 0
       0     .08       0   123.4    .045       0   133.4     .08       0
Bank Sta=123.4,133.4
XS Rating Curve= 0 ,0
Exp/Cntr=0.3,0.1

Type RM Length L Ch R = 1 ,203.3   ,184.1,183.5,183
XS GIS Cut Line= 3
     1803808.682      143052.005     1803859.749      142957.513
     1803922.828       142731.23
#Sta/Elev= 30
     9.8 1363.51    29.3 1363.86    48.8 1364.35    58.6 1364.51    68.4 1364.53
    78.1 1364.34    87.9 1363.94   107.4 1362.78   117.2 1361.66     127 1360.15
   136.8 1357.41   146.6  1353.4   151.3 1352.09   156.3 1350.68   161.3 1351.45
   166.1 1352.18   185.7 1362.22   195.5 1363.96   205.3 1363.73   215.1 1363.06
   224.9 1362.65   234.7 1362.62   244.4 1362.92   254.2 1363.35   273.8 1364.54
   283.6 1364.99   293.4 1365.25   303.2 1365.22     313 1364.83   342.3 1363.15
#Mann= 3 , 0 , 0
       0     .06       0   151.3    .045       0   161.3     .06       0
Bank Sta=151.3,161.3
XS Rating Curve= 0 ,0
Exp/Cntr=0.3,0.1

Type RM Length L Ch R = 1 ,19.8    ,20.1,19.8,19.5
XS GIS Cut Line= 4
       1803838.7      143074.614     1804034.676      143019.586
     1804066.535      142892.153      1803958.41      142742.516
#Sta/Elev= 30
     9.7 1364.83    29.1 1362.53    38.8 1361.93    48.5 1361.72     126 1361.75
   145.4 1361.24   155.1 1360.51   164.8 1359.26   174.5 1357.58   184.2 1355.47
   203.6 1350.03   233.9 1350.92     244 1350.92   254.1 1350.13   264.2 1349.02
   269.3 1348.92   274.3 1348.82   279.3 1349.35   294.5 1351.06   304.6 1351.36
   324.8 1350.54   334.9 1350.45   354.3 1354.98   373.8 1358.76   383.5 1360.16
   393.2 1361.04   412.6 1361.56   500.1 1361.65   509.8 1361.95   519.5 1363.09
#Mann= 3 , 0 , 0
     9.7     .06       0   269.3    .045       0   279.3     .06       0
#XS Ineff= 2 , 0
           239.6 1353.98  304.03         1353.51
Permanent Ineff=
       F       F
Bank Sta=269.3,279.3
XS Rating Curve= 0 ,0
Exp/Cntr=0.3,0.1
Stream Node=Sugarcamp Branch,Main            , 0 , 0 ,Upstream end
Stream Node=Sugarcamp Branch,Main            , 0 , 1 ,Downstream end

Chan Stop Cuts=-1
Use User Specified Reach Order=0